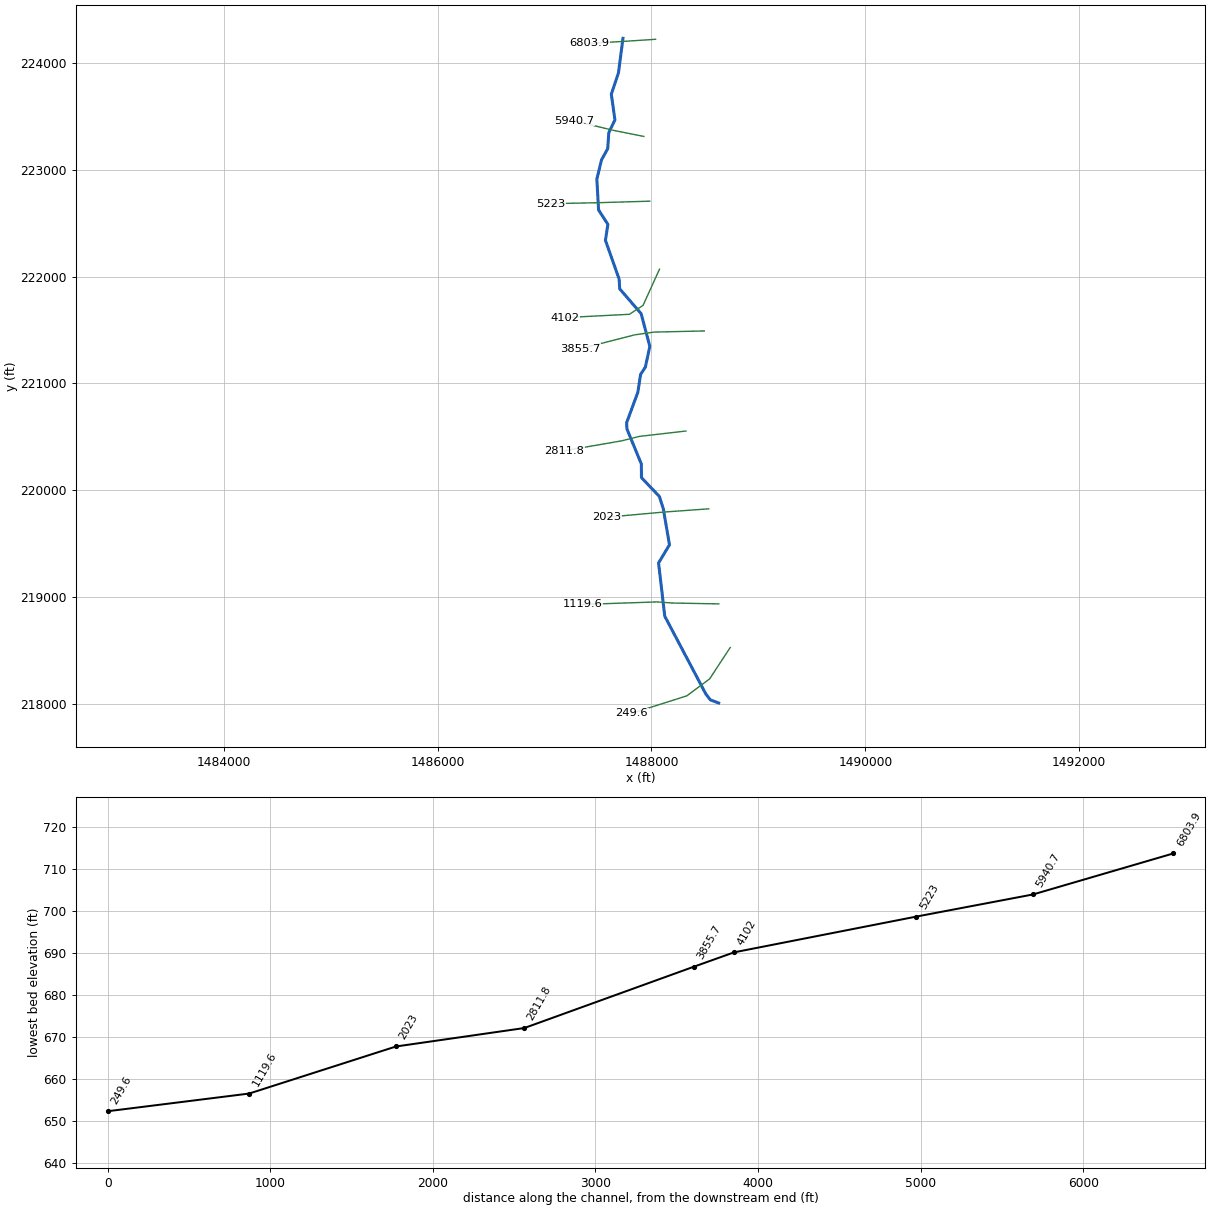
--- LFMCFRNCR.prj (project) ---

Proj Title=LFMCFRNCR
Current Plan=p01
Default Exp/Contr=0,0
English Units
Geom File=g01
Flow File=f01
Plan File=p01
BEGIN DESCRIPTION:
END DESCRIPTION:
DSS Export Rating Curves= 0
DSS Export Rating Curve Sorted= 0
DSS Export Volume Flow Curves= 0
DXF OffsetX= 0
DXF OffsetY= 0
DXF ScaleX= 0
DXF ScaleY= 0

--- LFMCFRNCR.p01 (plan) ---

Plan Title=Floodplain
Program Version=4.00
Geom File=g01
Flow File=f01
K Sum by GR=0
Std Step Tol=0.01
Critical Tol=0.01
Num of Std Step Trials=20
Max Error Tol=0.3
Flow Tol Ratio=0.001
Split Flow NTrial=30
Split Flow Tol=0.02
Split Flow Ratio=0.02
Log Output Level=0
Friction Slope Method=1
Unsteady Friction Slope Method=2
Unsteady Bridges Friction Slope Method=1
Global Log Level=0
CheckData=False
Run HTab=0
Run UNet=0
Run PostProcess=0
UNET Theta=0
UNET Theta Warmup=0
UNET ZTol=0
UNET ZSATol=0
UNET MxIter=0
UNET MaxInSteps=0
UNET DtIC=0
UNET DtMin=0
UNET MaxCRTS=0
UNET WFStab=0
UNET SFStab=0
UNET WFX=0
UNET SFX=0
UNET DSS MLevel=0
UNET DZMax Abort=0
UNET Convert EG Bridges=0
UNET Use Existing IB Tables=0
UNET Froude Limit=0
UNET Froude Power=0
Write IC File=0
Echo Input=False
Echo Output=False
Write Detailed=0

--- LFMCFRNCR.f01 (steady flow) ---

Flow Title=NFF Regression Equation
Program Version=4.10
Number of Profiles= 1
Profile Names=P100yr
River Rch & RM=LFMCFRNCR,Main            ,6803.9
888.4277
River Rch & RM=LFMCFRNCR,Main            ,5940.7
899.5371
River Rch & RM=LFMCFRNCR,Main            ,4102
957.4542
River Rch & RM=LFMCFRNCR,Main            ,3855.7
1163.099
River Rch & RM=LFMCFRNCR,Main            ,2811.8
1209.696
River Rch & RM=LFMCFRNCR,Main            ,249.6
1264.626
Boundary for River Rch & Prof#=LFMCFRNCR,Main            , 1
Up Type= 0
Dn Type= 3
Dn Slope=0.0048
DSS Import GetInterval= 0
DSS Import GetPeak= 0
DSS Import FillOption= 0

--- LFMCFRNCR.g01 (geometry) ---

Geom Title=USGS 10m DEM
Program Version=4.10

River Reach=LFMCFRNCR       ,Main
Reach XY= 30
     1487733.571      224234.201     1487691.383      223910.503
     1487624.717       223710.85     1487658.332      223469.618
      1487601.04      223350.347     1487590.884      223200.347
     1487532.655      223094.258     1487489.426      222915.091
     1487505.571      222626.028     1487592.551      222491.132
     1487569.634      222341.653     1487697.759      221978.111
     1487702.967      221886.966     1487903.488      221654.153
     1487984.738      221347.903     1487943.321      221154.457
     1487898.182      221084.318     1487872.835      220917.651
     1487767.974      220632.582     1487770.057       220575.29
     1487905.647      220244.822     1487906.516      220117.652
      1488074.05      219941.436     1488110.509      219826.853
     1488168.469      219488.399     1488066.489      219318.102
     1488124.409      218819.587     1488508.966      218089.373
     1488551.067      218035.119      1488628.64      218005.857

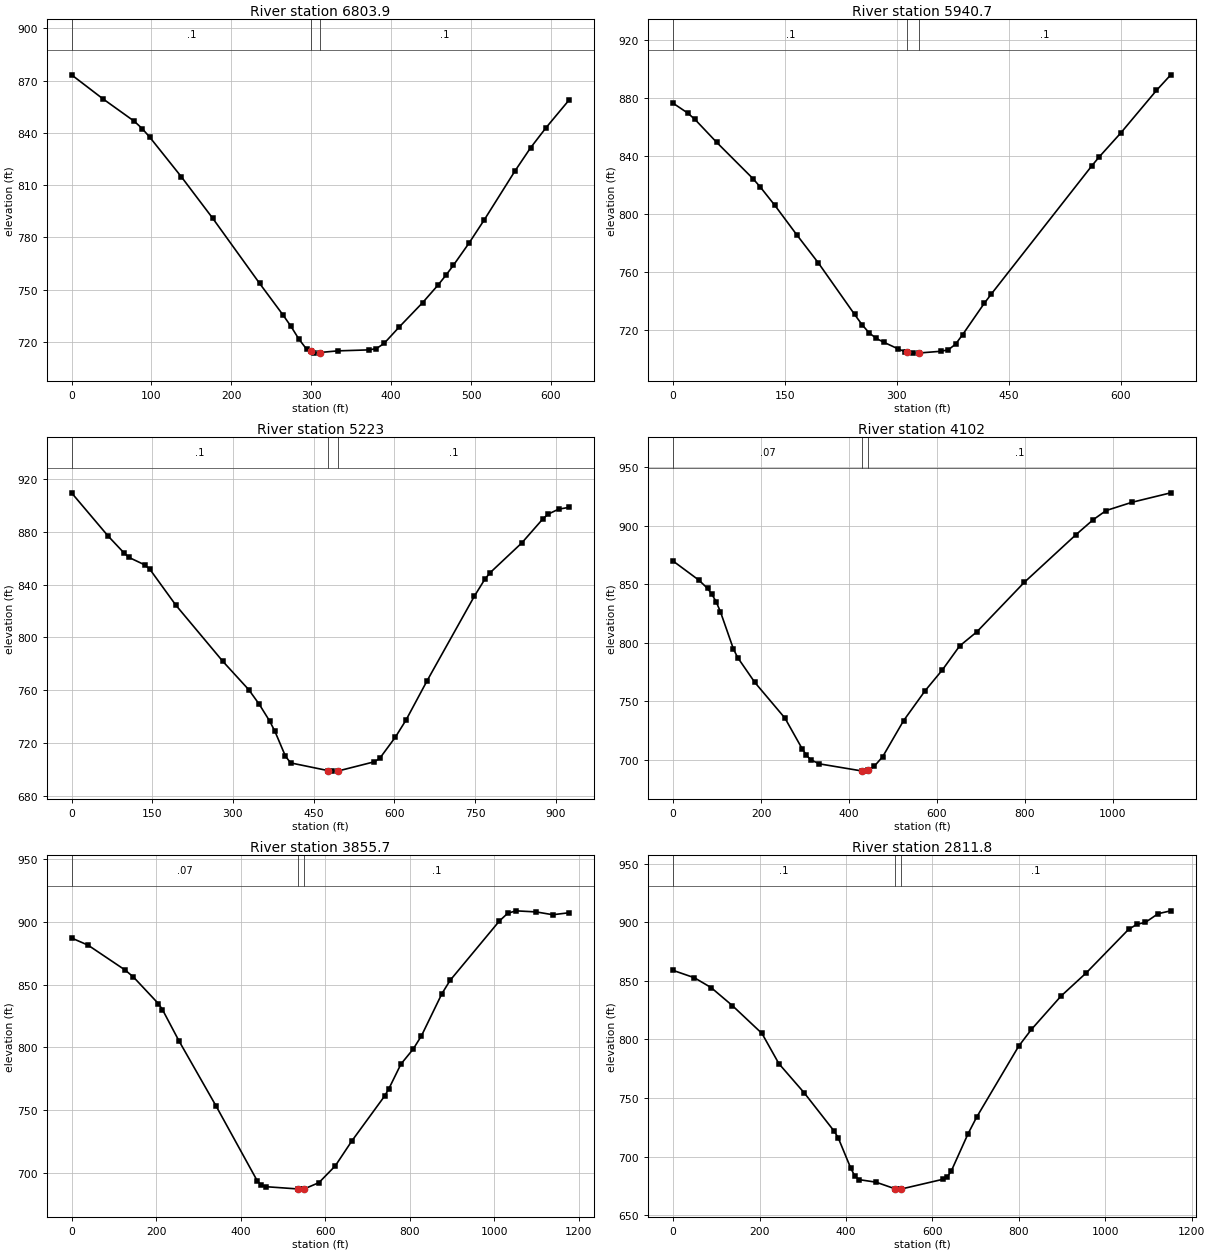
Type RM Length L Ch R = 1 ,6803.9  ,867.7,863.2,854.5
XS GIS Cut Line= 3
      1488038.56      224225.303     1487735.189      224205.235
     1487417.032      224187.109
#Sta/Elev= 30
       0  873.32    39.2  859.57    78.5  846.67    88.3  842.52    98.1   837.4
   137.3  814.87   176.5  791.11   235.4   753.6   264.8  735.42   274.6  728.98
   284.4  721.75   294.2  715.85  299.75714.5975     304  713.64   310.7     714
     333  714.93   371.6  715.49   381.3   716.2     391  719.17   410.3  728.76
   439.2  742.55   458.5  752.64   468.2  758.19   477.9   764.1   497.2  776.65
   516.5  790.15   555.1  818.31   574.4  831.46   593.7  842.96   622.7  858.93
#Mann= 3 , 0 , 0
       0      .1       0  299.75    .045       0   310.7      .1       0
Bank Sta=299.75,310.7
XS Rating Curve= 0 ,0
Exp/Cntr=0.3,0.1

Type RM Length L Ch R = 1 ,5940.7  ,709.5,717.6,721.1
XS GIS Cut Line= 3
     1487929.185       223315.06     1487642.727      223372.352
     1487278.143      223460.894
#Sta/Elev= 30
       0  876.38    19.5  869.64    29.2  865.26    58.4  849.39   107.1  824.33
   116.8   818.6   136.3  805.97   165.5  785.77   194.8  766.12   243.4  730.56
   253.2  723.62   262.9  717.84   272.7  713.99   282.4  711.42   301.8   706.8
   311.4  704.78   314.2  704.52     321  703.89   329.2  703.95   359.5  705.19
   369.1  706.22   378.7  710.06   388.3  716.73   417.2  738.26   426.8  744.77
   561.5  833.22   571.1  839.19     600  855.71   648.1  885.23   667.3     896
#Mann= 3 , 0 , 0
       0      .1       0   314.2    .045       0   329.2      .1       0
Bank Sta=314.2,329.2
XS Rating Curve= 0 ,0
Exp/Cntr=0.3,0.1

Type RM Length L Ch R = 1 ,5223    ,1107.1,1121,1132.6
XS GIS Cut Line= 3
     1487983.872       222708.29     1487499.447      222693.963
     1487059.393      222684.852
#Sta/Elev= 30
       0   909.6    67.8   876.9    96.9  864.29   106.6  860.65   135.7  855.05
   145.4  851.72   193.8  824.45   281.1  781.87   329.6  760.23   348.9  749.25
   368.3   736.5     378  728.73   397.4  710.05   407.1  704.87   477.1  698.99
   484.6  698.63   494.4  698.64   562.9  705.73   572.7  708.28     602  724.51
   621.6  737.36   660.7  767.11   748.7  831.32   768.3  844.25   778.1  849.14
   836.8  871.65   875.9  889.83   885.7  893.43   905.2  897.22   924.8   898.6
#Mann= 3 , 0 , 0
       0      .1       0   477.1    .045       0   494.4      .1       0
Bank Sta=477.1,494.4
XS Rating Curve= 0 ,0
Exp/Cntr=0.3,0.1

Type RM Length L Ch R = 1 ,4102    ,256.2,246.4,236.4
XS GIS Cut Line= 4
     1488075.018      222070.269     1487921.372      221731.727
     1487793.768      221648.394     1487186.997      221617.144
#Sta/Elev= 30
       0  869.85    58.7  853.51    78.3  846.45      88  841.55    97.8  835.11
   107.6  826.47     137  794.77   146.8  787.31   185.9  765.99   254.4  735.46
   293.5  709.23   303.3  703.74   313.1  699.78   332.6  696.35   429.2  690.28
   438.4  690.13   444.2  690.89   457.5  694.31   476.6  702.47   524.2  733.35
   573.2  758.95   612.4  776.74   651.6  797.21   690.8  809.31   798.6  851.63
   916.2  892.44   955.4  905.26   984.8  913.09  1043.6  920.16  1131.8  928.25
#Mann= 3 , 0 , 0
       0     .07       0   429.2    .045       0   444.2      .1       0
Bank Sta=429.2,444.2
XS Rating Curve= 0 ,0
Exp/Cntr=0.3,0.1

Type RM Length L Ch R = 1 ,3855.7  ,1039.6,1043.8,1044.5
XS GIS Cut Line= 4
     1488494.289      221492.144     1488025.539      221481.727
     1487843.247      221455.685     1487335.435      221325.477
#Sta/Elev= 30
       0  887.19    39.1  881.48     127  861.56   146.5  856.01   205.1  834.91
   214.9  830.12     254  805.13   341.9  753.07   439.6  693.17   449.3  689.84
   459.1  688.69   535.5  686.87   546.4  686.73   550.5  686.92   585.2   691.9
   623.9   705.3   662.7  725.01   740.4  760.95   750.1  766.51   779.2  786.54
   808.3  798.56   827.8  809.16   876.3  842.86   895.7  853.46  1012.2  900.81
  1031.6  906.87    1051  908.89  1099.6     908  1138.4  905.77  1177.2  907.37
#Mann= 3 , 0 , 0
       0     .07       0   535.5    .045       0   550.5      .1       0
Bank Sta=535.5,550.5
XS Rating Curve= 0 ,0
Exp/Cntr=0.3,0.1

Type RM Length L Ch R = 1 ,2811.8  ,791.1,788.8,783.3
XS GIS Cut Line= 4
     1488322.414      220554.644     1487884.777      220503.736
      1487726.06      220463.498     1487186.997      220369.748
#Sta/Elev= 30
       0  859.04      49   852.8    88.1   844.3   137.1  828.96   205.6  805.16
   244.8  779.31   303.5  754.34     372  721.97   381.8  716.16   411.2   689.9
     421  682.96   430.8  680.22   469.5  678.08   513.2  672.47   517.6  672.14
   528.2  672.27   623.9  680.51   633.6  682.31   643.4  687.42   682.5  719.51
     702  733.42   799.7  794.34     829  808.57   897.4  837.03   956.1  856.98
  1053.8  894.06  1073.3  898.46  1092.9  900.08  1122.2   907.5  1151.5  909.95
#Mann= 3 , 0 , 0
       0      .1       0   513.2    .045       0   528.2      .1       0
Bank Sta=513.2,528.2
XS Rating Curve= 0 ,0
Exp/Cntr=0.3,0.1

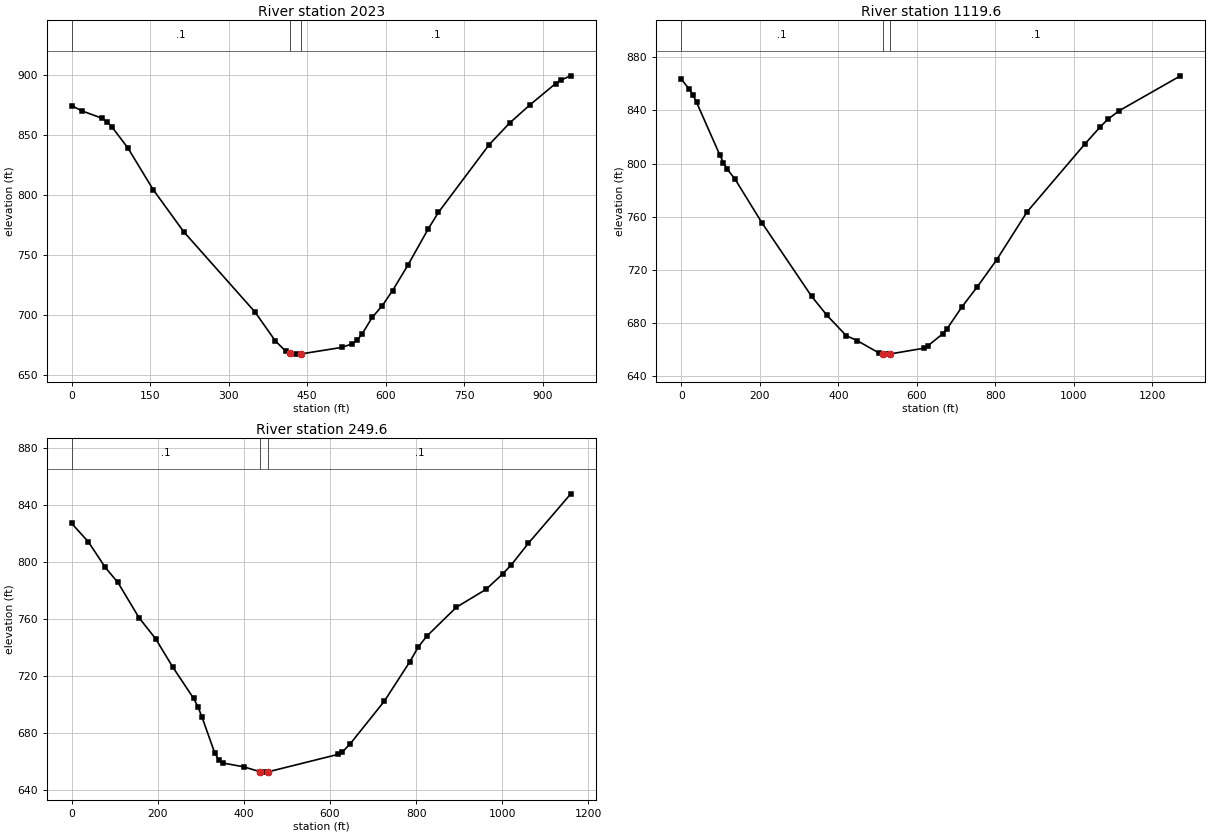
Type RM Length L Ch R = 1 ,2023    ,904.4,903.4,897.9
XS GIS Cut Line= 3
     1488535.956      219825.477     1488108.694      219794.587
     1487585.435      219747.352
#Sta/Elev= 30
       0  874.71    19.5  870.38    58.4  864.14    68.2  861.08    77.9  856.49
   107.1   839.7   155.8  804.77   214.2  769.67   350.5  702.77   389.4  678.67
   408.9  670.31  417.65668.4427   428.4  667.76   438.1  667.91   515.9  673.33
   535.4  676.23   545.1  679.14   554.9  684.43   574.3  698.31   593.8  708.25
   613.2  720.63   642.4  741.75   681.3  771.98   700.8  785.76   798.1  842.33
     837  860.23   875.9  875.41   924.6     893   934.3  895.93   953.8  899.52
#Mann= 3 , 0 , 0
       0      .1       0  417.65    .045       0   438.1      .1       0
Bank Sta=417.65,438.1
XS Rating Curve= 0 ,0
Exp/Cntr=0.3,0.1

Type RM Length L Ch R = 1 ,1119.6  ,853.1,870,887.6
XS GIS Cut Line= 4
     1488629.706      218934.852     1488200.018      218942.665
     1488051.585      218953.167     1487358.872      218929.644
#Sta/Elev= 30
       0  863.43    19.5  856.34    29.3  851.91    39.1  845.98    97.7  806.74
   107.4  800.65   117.2  795.71   136.7  788.37   205.1  755.59   332.1  700.02
   371.2  685.75     420  670.52   448.4  666.68   504.2  657.35   513.5  656.66
   522.8  656.57   532.1  656.71   617.6  660.99   627.4  662.64   666.4  671.92
   676.2  675.26   715.2  692.22   754.3   707.3   803.1  727.38   881.2  763.72
  1027.6   814.5  1066.7   827.4  1086.2  833.21  1115.5  839.73  1271.7  866.02
#Mann= 3 , 0 , 0
       0      .1       0   513.5    .045       0   532.1      .1       0
Bank Sta=513.5,532.1
XS Rating Curve= 0 ,0
Exp/Cntr=0.3,0.1

Type RM Length L Ch R = 1 ,249.6   ,235.3,249.6,262.6
XS GIS Cut Line= 4
     1488736.477      218525.998     1488543.768      218231.727
     1488330.227      218072.873     1487814.602       217908.81
#Sta/Elev= 30
       0  827.17    39.1  814.06    78.2  796.15   107.5   785.6   156.3  760.94
   195.4  745.93   234.5  726.33   283.4   704.1   293.1  698.41   302.9  690.86
   332.2  665.91     342  660.81   351.8  658.73   399.3  656.12   437.3  652.66
   446.8  652.37   456.3  652.59   617.9  664.79   627.7  666.18   647.4  672.47
   726.1  702.23   785.2   729.9   804.8  740.26   824.5  747.85   893.4  768.24
   962.2  780.78  1001.6  791.85  1021.3  798.16  1060.6  813.18    1159   847.9
#Mann= 3 , 0 , 0
       0      .1       0   437.3    .045       0   456.3      .1       0
Bank Sta=437.3,456.3
XS Rating Curve= 0 ,0
Exp/Cntr=0.3,0.1

Chan Stop Cuts=-1
Use User Specified Reach Order=0
Composite Channel Slope=5